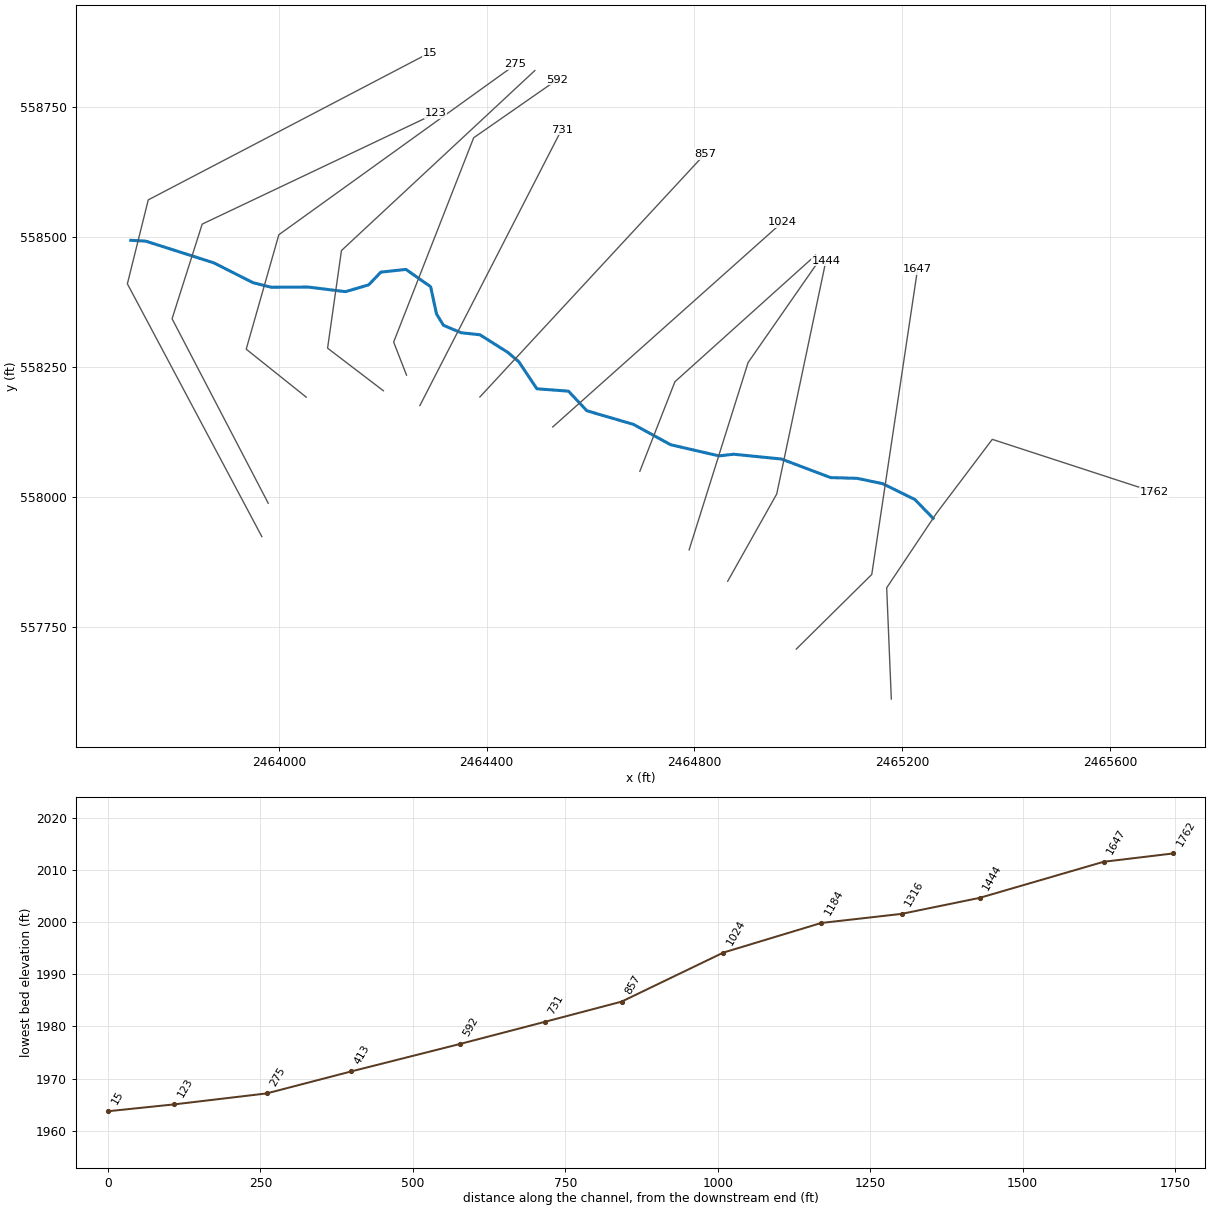
--- SENGRN.prj (project) ---

Proj Title=SENGRN
Current Plan=p01
Default Exp/Contr=0,0
English Units
Geom File=g01
Flow File=f01
Plan File=p01
BEGIN DESCRIPTION:
Stream Name: Seng Run
Flood Zone: Approximate
Pendleton County, West Virginia
HEC-RAS Version: 5.0.7
Hydrology Method:
Regression equation
END DESCRIPTION:
DSS Export Rating Curves= 0
DSS Export Rating Curve Sorted= 0
DSS Export Volume Flow Curves= 0
DXF OffsetX= 0
DXF OffsetY= 0
DXF ScaleX= 0
DXF ScaleY= 0

--- SENGRN.p01 (plan) ---

Plan Title=Floodplain
Program Version=5.07
Short Identifier=Floodplain
Geom File=g01
Flow File=f01
Subcritical Flow
K Sum by GR= 0
Std Step Tol= 0.01
Critical Tol= 0.01
Num of Std Step Trials= 20
Max Error Tol= 0.3
Flow Tol Ratio= 0.001
Split Flow NTrial= 30
Split Flow Tol= 0.02
Split Flow Ratio= 0.02
Log Output Level= 0
Friction Slope Method= 1
Unsteady Friction Slope Method= 2
Unsteady Bridges Friction Slope Method= 1
Parabolic Critical Depth
Global Vel Dist= 0 , 0 , 0
Global Log Level= 0
CheckData=True
Encroach Param=-1 ,0,0, 0
Mapping Interval=1HOUR
Computation Time Step Use Courant=        0
Computation Time Step Use Time Series=    0
Computation Time Step Count To Double=0
Computation Time Step Max Doubling=0
Computation Time Step Max Halving=0
Computation Time Step Residence Courant=0
Run HTab= 0
Run UNet= 0
Run Sediment= 0
Run PostProcess= 0
Run WQNet= 0
Run RASMapper= 0
UNET Theta= 0
UNET Theta Warmup= 0
UNET ZTol= 0
UNET ZSATol= 0
UNET MxIter= 0
UNET Max Iter WO Improvement= 0
UNET MaxInSteps= 0
UNET DtIC= 0
UNET DtMin= 0
UNET MaxCRTS= 0
UNET WFStab= 0
UNET SFStab= 0
UNET WFX= 1
UNET SFX= 1
UNET 1D Methodology=Finite Difference
UNET DSS MLevel= 1
UNET Pardiso=0
UNET DZMax Abort= 0
UNET Use Existing IB Tables= 0
UNET Froude Reduction=False
UNET Froude Limit= 0
UNET Froude Power= 0
UNET D1 Cores= 0
UNET D2 Coriolis=0
UNET D2 Cores= 0
UNET D2 Theta= 1
UNET D2 Theta Warmup= 1
UNET D2 Z Tol= 0.01
UNET D2 Volume Tol= 0.01
UNET D2 Max Iterations= 20
UNET D2 Equation= 0
UNET D2 RampUpFraction=0.1
UNET D2 TimeSlices= 1
UNET D2 BCVolumeCheck=0
UNET D1D2 MaxIter= 0
UNET D1D2 ZTol=0.01
UNET D1D2 QTol=0.1
UNET D1D2 MinQTol=1
Write IC File= 0
Write IC File at Fixed DateTime=0
Write IC File at Sim End=0
Echo Input=False
Echo Parameters=False
Echo Output=False
Write Detailed= 0
HDF Write Warmup=0
HDF Write Time Slices=0
HDF Flush=0
HDF Face Node Velocities=0
HDF Compression= 1
HDF Chunk Size= 1
HDF Spatial Parts= 1
HDF Use Max Rows=0
HDF Fixed Rows= 1
Calibration Method= 0
Calibration Iterations= 20
Calibration Max Change=0.05
Calibration Tolerance=0.2
Calibration Maximum=1.5
Calibration Minimum=0.5
Calibration Optimization Method= 1
WQ AD Non Conservative
WQ ULTIMATE=-1
WQ Max Comp Step=1HOUR
WQ Output Interval=15MIN
WQ Output Selected Increments= 0
WQ Output face flow=0
WQ Output face velocity=0
WQ Output face area=0
WQ Output face dispersion=0
WQ Output cell volume=0
WQ Output cell surface area=0
WQ Output cell continuity=0
WQ Output cumulative cell continuity=0
WQ Output face conc=0
WQ Output face dconc_dx=0
WQ Output face courant=0
WQ Output face peclet=0
WQ Output face adv mass=0
WQ Output face disp mass=0
WQ Output cell mass=0
WQ Output cell source sink temp=0
WQ Output nsm pathways=0
WQ Output nsm derived pathways=0
WQ Output MaxMinRange=-1
WQ Daily Max Min Mean=-1
WQ Daily Range=0
WQ Daily Time=0
WQ Create Restart=0
WQ Fixed Restart=0
WQ System Summary=0
WQ Write To DSS=0
WQ Use Fixed Temperature=0
Sorting and Armoring Iterations= 10
XS Update Threshold= 0.02
Bed Roughness Predictor= 0
Hydraulics Update Threshold= 0.02
Energy Slope Method= 1
Volume Change Method= 1
Sediment Retention Method= 0
XS Weighting Method= 0
Number of US Weighted Cross Sections= 1
Number of DS Weighted Cross Sections= 1
Upstream XS Weight=0
Main XS Weight=1
Downstream XS Weight=0
Number of DS XS's Weighted with US Boundary= 1
Upstream Boundary Weight= 1
Weight of XSs Associated with US Boundary= 0
Number of US XS's Weighted with DS Boundary= 1
Downstream Boundary Weight= 0.5
Weight of XSs Associated with DS Boundary= 0.5
Percentile Method= 0
Sediment Output Level= 3
Mass or Volume Output= 0
Output Increment Type= 1
Profile and TS Output Increment= 1
XS Output Flag= 0
XS Output Increment= 10
Write Gradation File= 0
Read Gradation Hotstart= 0
Write HDF5 File= 1
Write Binary Output= 1
Write DSS Sediment File= 0
SV Curve= 0
Specific Gage Flag= 0

--- SENGRN.f01 (steady flow) ---

Flow Title=Flows
Program Version=5.07
Number of Profiles= 6
Profile Names=P100yr,P10yr,P25yr,P50yr,P500yr,P101yr
River Rch & RM=SENGRN,Main            ,1762
     636     297     420     525     933     774
River Rch & RM=SENGRN,Main            ,413
     869     404     573     717    1280    1058
Boundary for River Rch & Prof#=SENGRN,Main            , 1
Up Type= 0
Dn Type= 3
Dn Slope=0.01231
Boundary for River Rch & Prof#=SENGRN,Main            , 2
Up Type= 0
Dn Type= 3
Dn Slope=0.01231
Boundary for River Rch & Prof#=SENGRN,Main            , 3
Up Type= 0
Dn Type= 3
Dn Slope=0.01231
Boundary for River Rch & Prof#=SENGRN,Main            , 4
Up Type= 0
Dn Type= 3
Dn Slope=0.01231
Boundary for River Rch & Prof#=SENGRN,Main            , 5
Up Type= 0
Dn Type= 3
Dn Slope=0.01231
Boundary for River Rch & Prof#=SENGRN,Main            , 6
Up Type= 0
Dn Type= 3
Dn Slope=0.01231
DSS Import GetInterval= 0
DSS Import GetPeak= 0
DSS Import FillOption= 0

--- SENGRN.g01 (geometry) ---

Geom Title=Geometry
Program Version=5.07

River Reach=SENGRN          ,Main
Reach XY= 30
2465259.48482507557958.6453742092465224.40387827557994.856259108
2465162.37749094558025.3677286212465112.92245063558035.639540255
 2465062.2031486558037.0233652592464967.52432811558072.771099254
 2464875.2819761558082.0379770552464847.42657289558078.801996261
2464754.24180561558100.3078215872464682.38091287558139.540304422
2464592.91566655558165.6953342712464557.48697838558203.431028843
2464496.68342206558208.0128350562464461.88909164558260.145703673
2464440.68290612558278.1315689382464387.08827767558311.992529318
2464351.01045617558315.8872656672464316.81063777558330.181104004
2464303.41335699 558352.182617592464292.16295055558404.472308725
2464244.63937718 558437.824534612464196.37803009 558432.63267006
2464172.72540453558407.9856691962464128.11225754558394.996134177
2464056.15035015558403.914627388 2463985.3940779558403.463937163
2463950.26697659 558412.268059822463874.70072076558450.469077945
2463743.59919778558492.2891354112463714.84599999558493.862000003

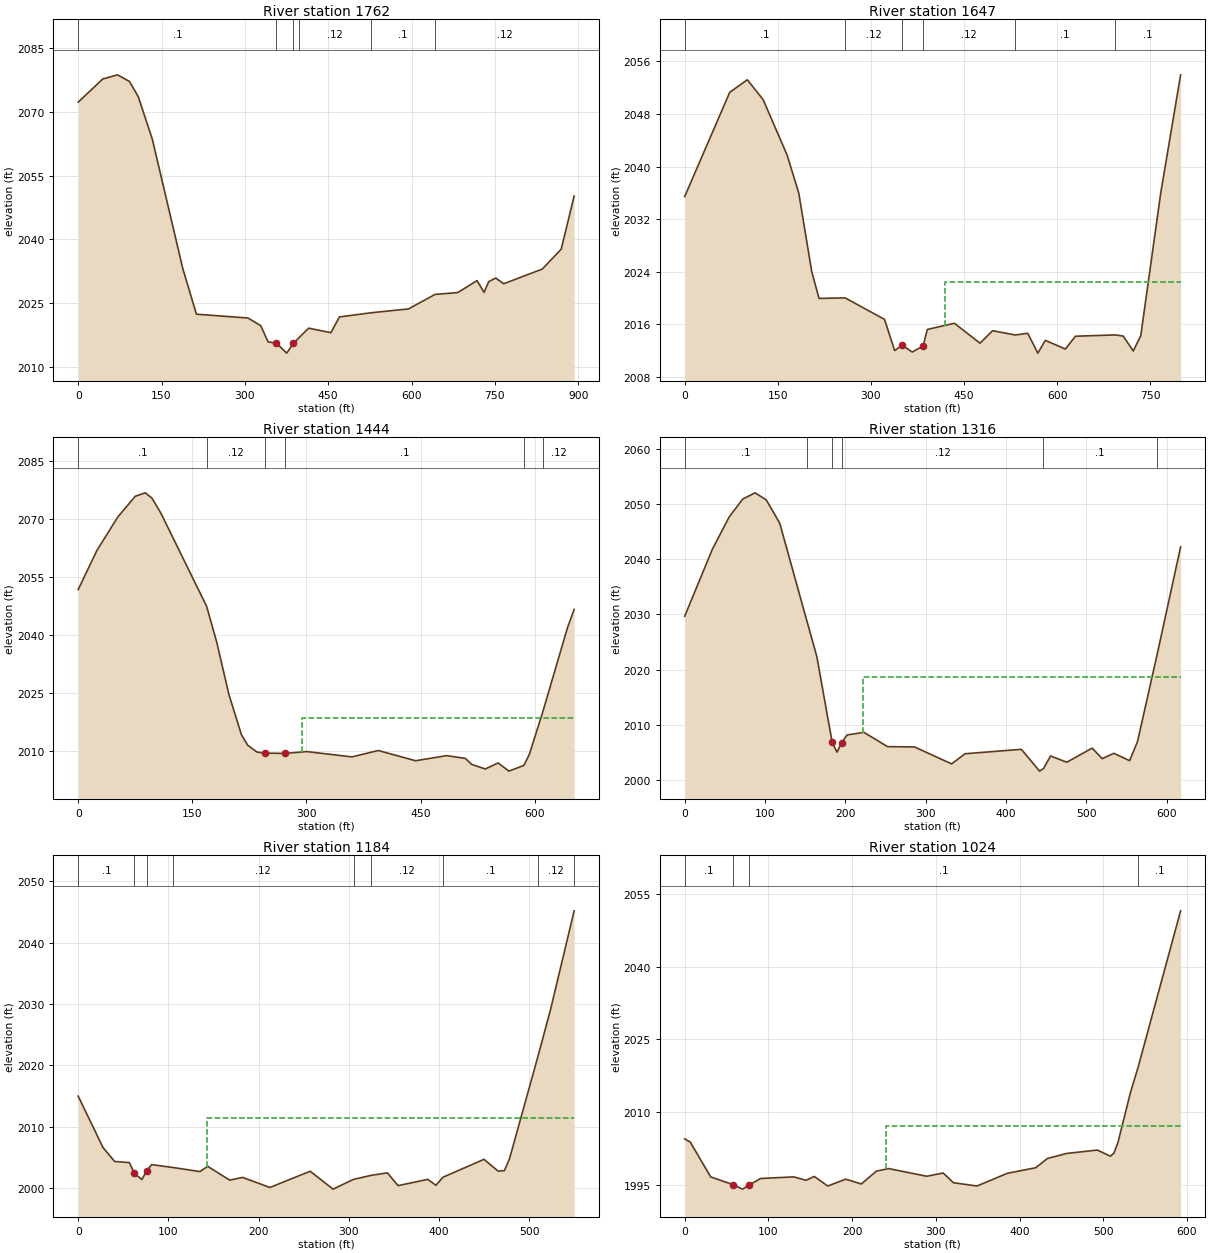
Type RM Length L Ch R = 1 ,1762    ,98.8,114.6,118.4
XS GIS Cut Line= 6
2465179.03049903557610.8140709262465170.09874444557824.898092709
2465259.49588875557958.6619290222465266.14666833557968.594681335
2465373.40826977558110.6649084892465684.88999589558009.086413385
#Sta/Elev= 30
       0 2072.26    44.1  2077.7    70.8 2078.69    92.2 2077.14   108.2 2073.52
   133.5 2063.52   188.2 2033.15   212.8 2022.39   305.6 2021.49   328.6  2019.7
   341.8 2015.87   356.72015.587   375.4 2013.23   387.1 2015.51   397.7 2016.89
   414.9  2019.1   454.9 2018.04   470.2 2021.74   526.3 2022.71   594.6 2023.63
   642.3 2027.04   683.4 2027.48     718 2030.29   730.6 2027.52     739 2030.05
   751.7 2030.89   765.9 2029.55   835.3 2032.99   869.5 2037.68   892.8 2050.18
#Mann= 6 ,-1 , 0
       0      .1       0   356.7    .045       0   387.1      .1       0
   397.7     .12       0   526.3      .1       0   642.3     .12       0
Bank Sta=356.7,387.1
XS Rating Curve= 0 ,0
Exp/Cntr(USF)=0,0
Exp/Cntr=0.3,0.1

Type RM Length L Ch R = 1 ,1647    ,205.4,203.4,202.7
XS GIS Cut Line= 3
2464996.01922119557706.8897826462465141.38350975557850.533232407
2465229.57881699558438.347393576
#Sta/Elev= 30
       0 2035.43    72.6 2051.29   100.9  2053.2   126.4 2050.17     165 2041.75
   183.8 2035.95   204.7 2023.99   216.4 2019.94   258.6 2020.02   321.9 2016.75
   338.2 2012.01   350.42012.815   366.5 2011.79     384 2012.69   390.8 2015.22
   434.5 2016.16   475.7 2013.13   495.9 2015.03   532.4 2014.38   552.6 2014.63
   568.8 2011.62   580.9 2013.56   613.2 2012.24   629.4 2014.19   693.3 2014.39
   706.3 2014.22   722.5 2011.95   734.6 2014.26   766.9 2036.05   798.8 2053.95
#Mann= 6 ,-1 , 0
       0      .1       0   258.6     .12       0   350.4    .045       0
     384     .12       0   532.4      .1       0   693.3      .1       0
#XS Ineff= 2 , 0
                          418.58         2022.42
Permanent Ineff=
       F       F
Bank Sta=350.4,384
XS Rating Curve= 0 ,0
Exp/Cntr=0.3,0.1

Type RM Length L Ch R = 1 ,1444    ,126.9,128,126.8
XS GIS Cut Line= 3
2464864.02832515557837.5057735192464958.41697297558005.444079716
2465053.19886861558454.840998698
#Sta/Elev= 30
       0 2051.77    24.5 2061.88    52.1  2070.6      75 2075.96    88.2 2076.85
      97 2075.46   108.8 2071.53   168.8 2047.43   182.2 2038.04   198.2 2024.48
   214.6 2014.12   222.7 2011.43     235 2009.64   245.9 2009.36   271.8 2009.28
   300.4 2009.76   359.9 2008.38   394.4 2010.04   443.5 2007.38   484.4 2008.71
   508.9 2007.99   517.1 2006.45   535.1 2005.25     552 2006.81   566.1 2004.69
   585.8 2006.17     593 2009.02   611.1 2020.34   643.1 2041.86   651.9 2046.62
#Mann= 6 ,-1 , 0
       0      .1       0   168.8     .12       0   245.9    .045       0
   271.8      .1       0   585.8     .12       0   611.1     .12       0
#XS Ineff= 2 , 0
                          294.48         2018.41
Permanent Ineff=
       F       F
Bank Sta=245.9,271.8
XS Rating Curve= 0 ,0
Exp/Cntr(USF)=0,0
Exp/Cntr=0.3,0.1

Type RM Length L Ch R = 1 ,1316    ,132.6,131.8,131
XS GIS Cut Line= 3
2464789.78344613557898.0016008712464903.26079239558258.513757798
2465039.94813984558455.019456063
#Sta/Elev= 30
       0 2029.68    34.5 2041.83    55.4 2047.67    72.2  2050.9    87.6 2052.04
   101.6 2050.75   118.3 2046.54   151.9 2028.94   164.5 2022.37   183.62006.837
   189.6 2005.06   195.22006.742   202.2 2008.18   223.2 2008.64   252.5 2006.06
   286.1    2006   332.2 2002.93     349 2004.77   419.1 2005.57   441.8 2001.62
   446.6 2002.08   455.4 2004.37   475.6 2003.23   507.2 2005.79   519.7 2003.88
   534.3 2004.85   553.8 2003.51   563.6 2006.95   587.9 2022.63   617.3 2042.25
#Mann= 6 ,-1 , 0
       0      .1       0   151.9     .12       0   183.6    .045       0
   195.2     .12       0   446.6      .1       0   587.9      .1       0
#XS Ineff= 2 , 0
                          221.47          2018.7
Permanent Ineff=
       F       F
Bank Sta=183.6,195.2
XS Rating Curve= 0 ,0
Exp/Cntr(USF)=0,0
Exp/Cntr=0.3,0.1

Type RM Length L Ch R = 1 ,1184    ,167.4,160.4,154
XS GIS Cut Line= 3
 2464694.9149896 558049.241169252464762.36787919558221.532814909
2465033.42138373558465.355914727
#Sta/Elev= 30
       0 2015.01    27.5 2006.64    40.4 2004.37    56.7 2004.19    62.3 2002.44
    70.5 2001.43    75.82002.814    81.4 2003.86   104.9 2003.39   134.9 2002.73
   143.5 2003.58   167.8 2001.34   182.2 2001.78   212.4 2000.14   257.1 2002.78
   282.4 1999.87   305.2 2001.46   324.6 2002.11   342.6 2002.52   354.5 2000.44
   387.4 2001.46   396.4  2000.5   404.3 2001.81   449.7 2004.72   465.3 2002.81
   472.3 2002.88     478 2004.83   509.1 2021.28   523.3 2029.02   549.6 2045.18
#Mann= 9 ,-1 , 0
       0      .1       0    62.3    .045       0    75.8      .1       0
   104.9     .12       0   305.2      .1       0   324.6     .12       0
   404.3      .1       0   509.1     .12       0   549.6    .045       0
#XS Ineff= 2 , 0
                          143.03         2011.38
Permanent Ineff=
       F       F
Bank Sta=62.3,75.8
XS Rating Curve= 0 ,0
Exp/Cntr=0.3,0.1

Type RM Length L Ch R = 1 ,1024    ,162.8,167,166.4
XS GIS Cut Line= 2
2464527.17655922 558134.485289612464969.31814416558528.762931303
#Sta/Elev= 30
       0 2004.53     6.6 2003.89    31.1  1996.7    57.81995.123    69.1 1994.19
    76.81995.031    90.8 1996.38   130.3 1996.71   144.9 1996.01   154.8  1996.8
   170.9 1994.83   192.4 1996.24     211 1995.25     229 1997.89   243.6 1998.42
   289.1 1996.84   308.8 1997.51     321 1995.51   349.2 1994.83   385.3 1997.44
   419.3 1998.59   433.3 2000.49   456.1 2001.53   492.9 2002.23   508.6 2000.96
   512.8 2001.62   517.5 2003.76   532.6 2014.14   541.5  2019.2   592.4 2051.46
#Mann= 4 ,-1 , 0
       0      .1       0    57.8    .045       0    76.8      .1       0
   541.5      .1       0
#XS Ineff= 2 , 0
                          240.84         2007.11
Permanent Ineff=
       F       F
Bank Sta=57.8,76.8
XS Rating Curve= 0 ,0
Exp/Cntr=0.3,0.1

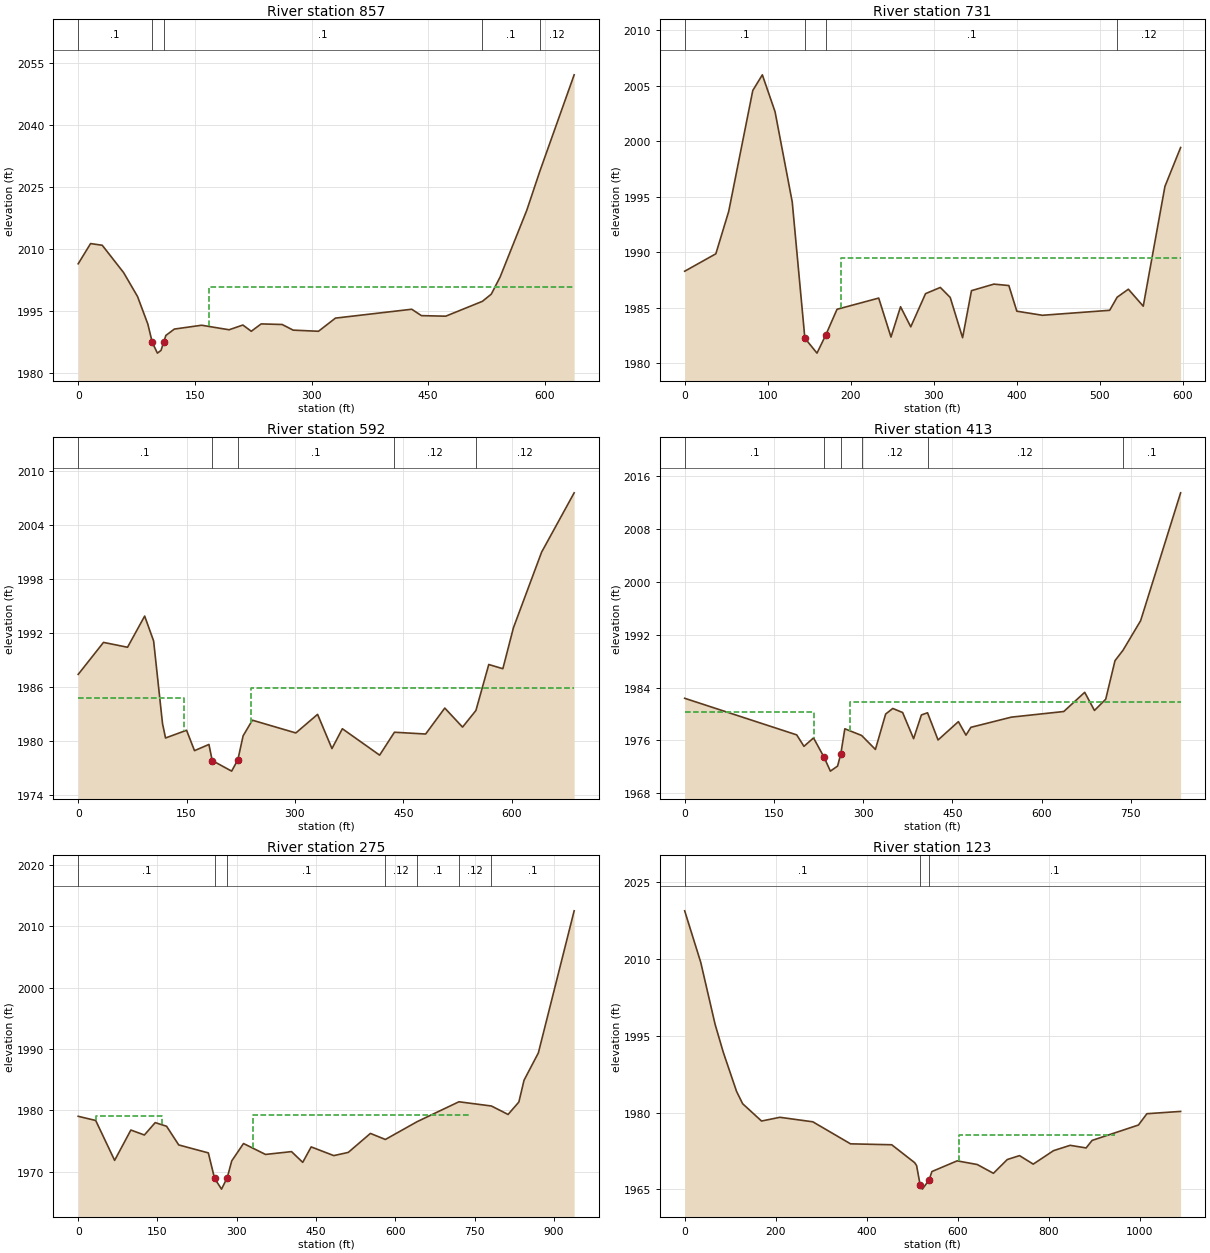
Type RM Length L Ch R = 1 ,857     ,123.2,125.9,129.1
XS GIS Cut Line= 2
2464386.93623217558192.2313066282464820.13986515558660.072553811
#Sta/Elev= 30
       0 2006.39    15.9 2011.28    30.9 2010.87    58.4 2004.25    76.3 1998.46
    89.5 1991.81    95.2 1987.38   101.8 1984.77   106.5 1985.44   109.71987.354
   112.7 1989.05   123.6 1990.59   158.7 1991.52     194 1990.42   211.7 1991.57
   222.5 1990.06   235.2 1991.84   262.2  1991.7   276.4 1990.33   308.9 1990.06
   330.7 1993.24   428.8 1995.39   441.3 1993.84   472.5 1993.71   519.7 1997.31
   531.1 1999.05   542.4 2003.18   576.7 2019.34   593.3 2028.68   637.6 2052.11
#Mann= 5 ,-1 , 0
       0      .1       0    95.2    .045       0   109.7      .1       0
   519.7      .1       0   593.3     .12       0
#XS Ineff= 2 , 0
                           168.1         2000.69
Permanent Ineff=
       F       F
Bank Sta=95.2,109.7
XS Rating Curve= 0 ,0
Exp/Cntr=0.3,0.1

Type RM Length L Ch R = 1 ,731     ,134.9,139.2,146.2
XS GIS Cut Line= 2
2464271.44419814558175.732444623 2464544.2098742558706.884731081
#Sta/Elev= 30
       0 1988.27    37.5 1989.84      53 1993.66      82 2004.56    93.5 2005.97
   108.8 2002.65   129.5 1994.51   144.71982.236   159.3 1980.89   169.81982.511
   183.4 1984.84   233.6 1985.85   248.4 1982.34   259.9 1985.07   272.2 1983.26
     290 1986.25   307.8 1986.81   319.7 1985.91   334.6 1982.28   345.3 1986.52
   372.3 1987.11   390.3 1986.98   399.9 1984.67   430.7  1984.3   511.7 1984.75
   520.7 1985.93   534.2 1986.65   552.1 1985.12   578.2 1995.91   597.1 1999.42
#Mann= 4 ,-1 , 0
       0      .1       0   144.7    .045       0   169.8      .1       0
   520.7     .12       0
#XS Ineff= 2 , 0
                          187.73         1989.47
Permanent Ineff=
       F       F
Bank Sta=144.7,169.8
XS Rating Curve= 0 ,0
Exp/Cntr=0.3,0.1

Type RM Length L Ch R = 1 ,592     ,169.1,178.4,181.3
XS GIS Cut Line= 4
2464245.68003835558234.2852843292464220.93739511558297.942129651
2464374.99465568558691.2867385822464535.79533642 558803.10541229
#Sta/Elev= 30
       0 1987.41      35 1990.97    68.3 1990.43      92  1993.9   104.4 1991.13
   116.7 1981.94   120.9 1980.33     150 1981.19     161 1978.92     181 1979.61
   185.51977.819   212.4 1976.64     221  1977.9   228.3 1980.57   241.1 1982.31
   301.3 1980.89   331.4 1982.96   351.3 1979.15   365.7 1981.36   417.3 1978.42
   437.8 1980.97     481 1980.77   507.5 1983.66   532.1 1981.54   550.6 1983.39
   568.4 1988.51   587.9 1988.04   602.5 1992.59   641.5 2001.01   686.6 2007.62
#Mann= 5 ,-1 , 0
       0      .1       0   185.5    .045       0     221      .1       0
   437.8     .12       0   550.6     .12       0
#XS Ineff= 2 , 0
          146.01 1984.77  238.65         1985.91
Permanent Ineff=
       F       F
Bank Sta=185.5,221
XS Rating Curve= 0 ,0
Exp/Cntr=0.3,0.1

Type RM Length L Ch R = 1 ,413     ,141.8,138.6,137.8
XS GIS Cut Line= 4
2464201.16688296558204.2131926872464093.74478061558286.215151009
 2464120.4567977558474.151111771 2464492.7533145558820.683913636
#Sta/Elev= 30
       0 1982.38   188.3 1976.85   200.5 1975.12   216.6 1976.39   234.31973.466
   244.9 1971.37     257 1972.13   262.41973.967   269.2 1977.77   297.4 1976.76
   320.6 1974.65   337.8    1980   349.8 1980.84   366.3 1980.23   384.8 1976.28
   397.9 1979.86   408.2 1980.19   425.9 1976.08   460.1 1978.85   472.8 1976.81
   481.1 1977.99   549.1 1979.53   637.2 1980.38   672.4 1983.28   688.8 1980.54
   707.7 1982.24   723.3 1988.06     737 1989.67   766.4 1994.11   833.6 2013.43
#Mann= 6 ,-1 , 0
       0      .1       0   234.3    .045       0   262.4      .1       0
   297.4     .12       0   408.2     .12       0     737      .1       0
#XS Ineff= 2 , 0
          216.87 1980.32  277.11         1981.79
Permanent Ineff=
       F       F
Bank Sta=234.3,262.4
XS Rating Curve= 0 ,0
Exp/Cntr=0.3,0.1

Type RM Length L Ch R = 1 ,275     ,153,151.4,151.4
XS GIS Cut Line= 4
2464052.58313639558191.9682872692463937.08482164558284.264184537
2463999.90741155558504.6014680782464455.66325269558832.427693156
#Sta/Elev= 30
       0 1979.03    33.1 1978.35    68.9 1971.84    99.6 1976.79   125.2 1975.98
   145.7    1978   167.2 1977.41   190.2 1974.36   246.2 1973.06     2581968.905
   271.2 1967.15     2821969.027   290.5 1971.76   312.8 1974.59   354.4 1972.81
   403.6 1973.27   424.8 1971.52   440.8 1974.04   483.6 1972.62     511 1973.14
   552.9 1976.24   581.2 1975.25   641.2 1978.15   720.4  1981.4   781.9 1980.71
   813.4 1979.33   833.8 1981.36   843.6 1984.92   870.7 1989.38   938.4 2012.55
#Mann= 7 ,-1 , 0
       0      .1       0     258    .045       0     282      .1       0
   581.2     .12       0   641.2      .1       0   720.4     .12       0
   781.9      .1       0
#XS Ineff= 2 ,-1
      33     159    1979  330.43  739.111979.248
Permanent Ineff=
       F       F
Bank Sta=258,282
XS Rating Curve= 0 ,0
Exp/Cntr(USF)=0,0
Exp/Cntr=0.3,0.1

Type RM Length L Ch R = 1 ,123     ,107.4,108.8,109.3
XS GIS Cut Line= 4
2463979.45220794557987.6924804292463794.36253602558342.823237262
 2463852.3170566558525.0307197022464302.38365416558738.642228682
#Sta/Elev= 30
       0 2019.37    35.2 2009.35    66.8 1997.24    84.8 1991.77     114 1984.13
   127.4 1981.72   168.9 1978.34   209.2 1979.07   281.6 1978.19   364.5 1973.89
     455 1973.71   505.5 1970.21   509.7 1969.64   517.31965.953   522.3 1965.05
     5371966.811   543.3 1968.48   598.8 1970.57   643.1 1969.85   678.5 1968.14
     709 1970.83   735.9 1971.59     766 1969.93   810.6 1972.56   847.1  1973.6
   882.2 1973.09   895.4 1974.56   997.2 1977.56  1015.8 1979.77  1089.9 1980.22
#Mann= 3 ,-1 , 0
       0      .1       0   517.3    .045       0     537      .1       0
#XS Ineff= 1 ,-1
  602.63   946.6 1975.55
Permanent Ineff=
       F
Bank Sta=517.3,537
XS Rating Curve= 0 ,0
Exp/Cntr(USF)=0,0
Exp/Cntr=0.3,0.1

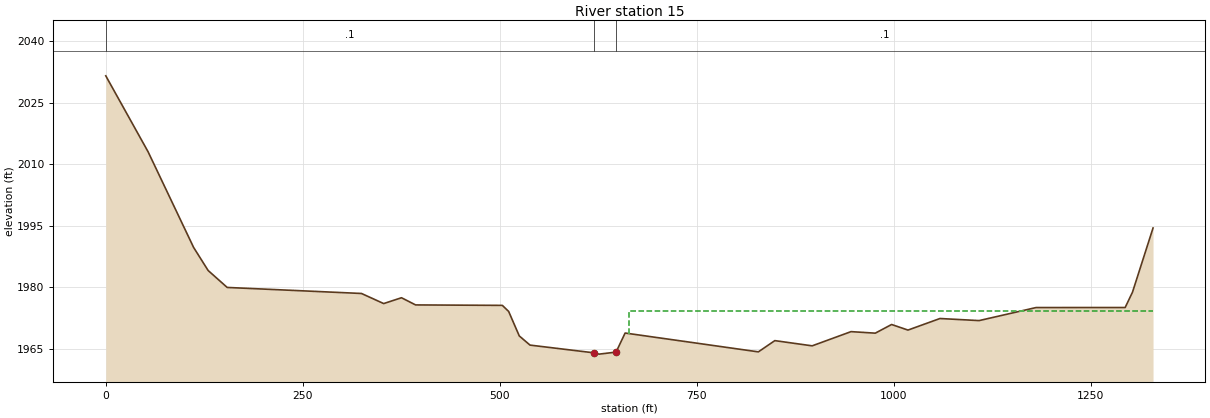
Type RM Length L Ch R = 1 ,15      ,,,
XS GIS Cut Line= 4
2463967.11770075557923.5180404612463708.31261084558410.071609506
2463748.50877068558571.669957971 2464290.4149357  558855.0016077
#Sta/Elev= 30
       0 2031.55    53.7 2013.04   111.5 1989.72   129.9 1984.11   154.1 1979.98
   324.5 1978.51   352.7 1976.05   375.3 1977.47   393.2 1975.72   503.3 1975.61
   511.3 1974.13   524.8 1968.16   538.4 1965.93   620.2 1964.03   626.1 1963.73
   647.6 1964.22   659.1 1968.87   828.2 1964.28   849.1 1967.02   896.5 1965.75
   945.8 1969.21   976.6 1968.84   997.3 1970.95  1018.1 1969.59  1058.7 1972.41
  1108.3  1971.9  1180.6 1975.08  1293.7 1975.09    1303 1978.82  1329.1 1994.47
#Mann= 3 ,-1 , 0
       0      .1       0   620.2    .045       0   647.6      .1       0
#XS Ineff= 2 , 0
                          663.74         1974.34
Permanent Ineff=
       F       F
Bank Sta=620.2,647.6
XS Rating Curve= 0 ,0
Exp/Cntr(USF)=0,0
Exp/Cntr=0.3,0.1
LCMann Table=0

Chan Stop Cuts=-1
Use User Specified Reach Order=0
Composite Channel Slope=5